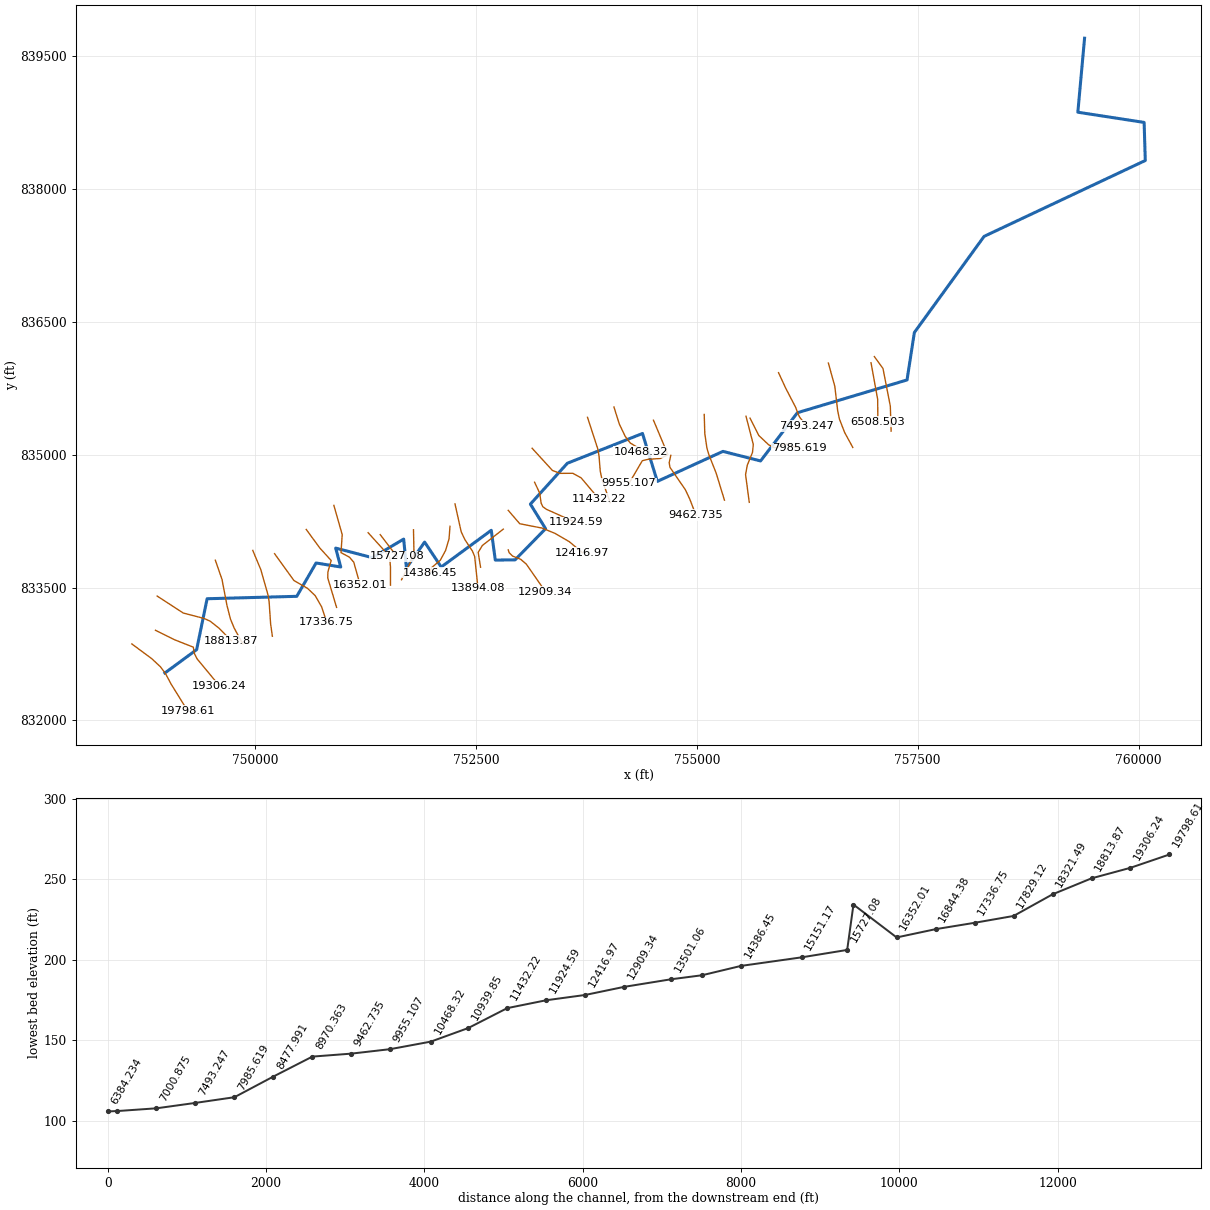
--- 15526_ras.prj (project) ---

Proj Title=15526
Current Plan=p01
Default Exp/Contr=0.3,0.1
English Units
Geom File=g01
Flow File=f01
Plan File=p01
Y Axis Title=Elevation
X Axis Title(PF)=Main Channel Distance
X Axis Title(XS)=Station
BEGIN DESCRIPTION:
RFD model 15526 exported to HEC-RAS
END DESCRIPTION:

--- 15526_ras.p01 (plan) ---

Plan Title=Plan 01
Program Version=4.10
Short Identifier=Plan 01
Geom File=g01
Flow File=f01
Subcritical Flow
Calc Critical at every XS
Secant Critical Depth

--- 15526_ras.f01 (steady flow) ---

Flow Title=Flow 01
Program Version=5.01
Number of Profiles= 6
Profile Names=10yr,25yr,50yr,100yr,100plus,500yr
River Rch & RM=15526,33,19798.61
 1133.03 1844.88 2523.35 3149.21 4597.85 6185.35
River Rch & RM=15526,33,19306.24
 1140.16 1856.82    2540 3170.32 4628.67 6222.37
River Rch & RM=15526,33,18813.87
 1160.31 1890.59 2587.08 3230.01 4715.82 6326.78
River Rch & RM=15526,33,18321.49
 1165.44 1899.22 2599.14 3245.34  4738.2  6353.7
River Rch & RM=15526,33,17829.12
 1184.05 1930.53 2642.91 3300.96  4819.4  6451.2
River Rch & RM=15526,33,17336.75
  1191.7  1943.4 2660.91 3323.83 4852.79 6491.25
River Rch & RM=15526,33,16844.38
 1200.03 1957.42 2680.51 3348.74 4889.16 6534.83
River Rch & RM=15526,33,16352.01
 1207.79 1970.53 2698.87 3372.13  4923.3 6575.88
River Rch & RM=15526,33,15806.58
  1213.7 1980.53 2712.89 3389.98 4949.37 6607.21
River Rch & RM=15526,33,15727.08
 1214.61 1982.06 2715.04 3392.72 4953.38 6612.02
River Rch & RM=15526,33,15151.17
 1220.07 1991.28 2727.96 3409.18  4977.4 6640.88
River Rch & RM=15526,33,14386.45
 1870.34 3069.96  4222.9 5293.64 7728.71 9752.22
River Rch & RM=15526,33,13894.08
  1875.3 3078.34 4234.67 5308.66 7750.64    9777
River Rch & RM=15526,33,13501.06
 1878.59 3083.93 4242.52 5318.66 7765.25 9793.51
River Rch & RM=15526,33,12909.34
 1905.12 3128.87 4305.65 5399.18  7882.8  9926.2
River Rch & RM=15526,33,12416.97
  1924.8 3162.21 4352.48 5458.93 7970.03 10024.5
River Rch & RM=15526,33,11924.59
  1928.9 3169.15 4362.23 5471.36 7988.1910044.92
River Rch & RM=15526,33,11432.22
 2569.25 4241.87  5858.9 7368.42 10757.913045.02
River Rch & RM=15526,33,10939.85
 2575.83    4253 5874.53 7388.35   1078713076.34
River Rch & RM=15526,33,10468.32
 2608.69  4308.5 5952.39 7487.5110931.7613231.57
River Rch & RM=15526,33,9955.107
 2612.53 4315.01 5961.54 7499.18 10948.813249.89
River Rch & RM=15526,33,9462.735
 2631.74 4347.64 6007.47 7557.8411034.4513342.27
River Rch & RM=15526,33,8970.363
 2764.47  4570.8 6319.63 7954.3411613.3313955.17
River Rch & RM=15526,33,8477.991
 2772.57 4584.56 6338.99 7979.0511649.4213993.74
River Rch & RM=15526,33,7985.619
 2783.37 4602.95 6364.92 8012.2211697.8514045.69
River Rch & RM=15526,33,7493.247
 2840.72  4699.9 6501.01 8185.62   1195114314.13
River Rch & RM=15526,33,7000.875
 2863.59 4738.79 6555.81 8255.6712053.2814423.26
River Rch & RM=15526,33,6508.503
 2871.38 4752.06  6574.5 8279.5612088.1614460.44
River Rch & RM=15526,33,6384.234
 2871.94    4753 6575.83 8281.2712090.65 14463.1
River Rch & RM=15526,33,5990.745
 2876.95 4761.52 6587.83 8296.6112113.0614486.98
Boundary for River Rch & Prof#=15526,33,1
Up Type= 0
Dn Type= 2
Boundary for River Rch & Prof#=15526,33,2
Up Type= 0
Dn Type= 2
Boundary for River Rch & Prof#=15526,33,2
Up Type= 0
Dn Type= 2
Boundary for River Rch & Prof#=15526,33,2
Up Type= 0
Dn Type= 2
Boundary for River Rch & Prof#=15526,33,2
Up Type= 0
Dn Type= 2
Boundary for River Rch & Prof#=15526,33,2
Up Type= 0
Dn Type= 2

--- 15526_ras.g01 (geometry) ---

Geom Title=15526
Program Version=4.10

River Reach=15526,33
Reach XY= 30
748982.319855452  832535.3326969749341.448685825832798.969444826
749459.938269168833373.188194826750474.261185825833400.531944811
750693.011185825833776.834028125750971.657019198833731.261111498
750914.365352511833944.802778155751329.729935795833836.729861483
751683.896602511834046.365278155751715.146602511833720.844444826
751920.875769138834012.511111468752108.375769138833731.261111498
752674.782019138834145.323611483752720.354935825833809.386111498
752944.313269138 833811.99027814753289.365352511834163.552778155
753117.490352511 834440.89652817753535.459102422834901.834028125
754385.719519138 835237.77152817754553.688269168834697.406944782
755295.875769168835035.948611498755721.657019109834927.875694811
756138.323685825 835472.14652814757378.902019709835841.987460062
 757461.68089807836377.346844345758250.743398011837461.982260987
760074.344494969838318.030067787760061.323661685838747.717567801
759311.411002964838862.820667744759387.331922799839697.920241743

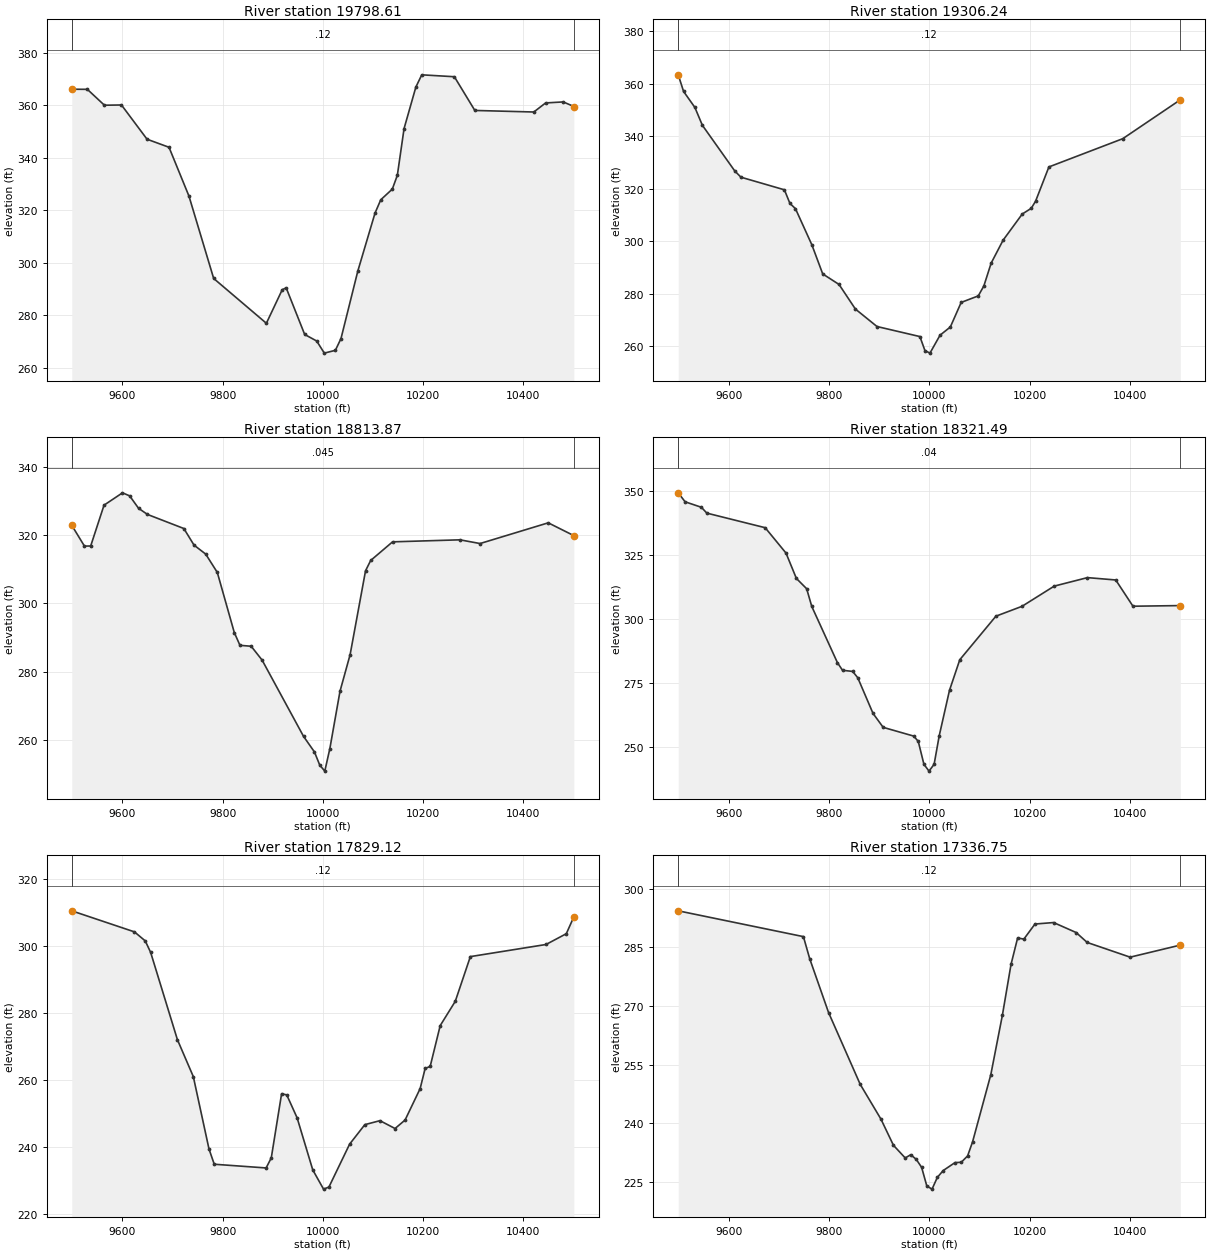
Type RM Length L Ch R = 1 ,19798.61,492.371900,492.371900,492.371900
XS GIS Cut Line= 6
748608.075291165832863.246064497748832.725400942 832697.59619237
748931.724107291832605.526841969748988.405081861832530.050481327
749051.583849095832411.896254622749240.693166295832107.141807371
#Sta/Elev= 30
9499.081366.08449530.147366.0419  9564.2359.99429598.253360.08239649.333347.0345
9693.122343.97289732.953325.35799782.239294.00559887.396276.93259918.975289.6942
9926.897290.44489963.844272.66879987.849270.173710002.99265.5648 10025.1266.6355
10036.31271.124510069.92296.866610104.19318.905510115.69323.9821 10138.7328.0376
10148.75333.305610162.15351.092910185.69366.901310197.46371.566910262.54 370.839
10303.38357.997210421.07357.406710444.61360.861410479.91361.245310500.93359.4993
#Mann= 3 , 0 , 0
9499.081    0.12       09499.081    0.12       010500.93    0.12       0
#XS Ineff= 2 , 0
       0                               0
Bank Sta=9499.081,10500.93
Exp/Cntr=0.3,0.1

Type RM Length L Ch R = 1 ,19306.24,492.372000,492.372000,492.372000
XS GIS Cut Line= 6
 748875.55480692833017.314036452749090.849469856832910.772153159
749303.832014661832826.693323594749316.111578053832755.129584077
749346.118087025832695.409618627749596.187181603832393.831705638
#Sta/Elev= 30
9499.255363.42639509.917357.08729532.492350.98059547.362344.19639612.039326.7584
9624.391324.37929711.037319.57189722.063314.38589733.088312.38219765.765298.6177
9787.485287.49099820.066283.46669852.646274.09699895.737267.42939981.358 263.595
9991.376258.2672 10001.4257.279510021.57264.126710042.07267.244710063.68276.6158
 10097.8279.109410108.93282.891810123.49291.601110147.31300.355710185.56310.3381
10203.42312.507510212.12315.223310238.69328.295110386.01339.066410500.85353.9021
#Mann= 3 , 0 , 0
9499.255    0.12       09499.255    0.12       010500.85    0.12       0
#XS Ineff= 2 , 0
       0                               0
Bank Sta=9499.255,10500.85
Exp/Cntr=0.3,0.1

Type RM Length L Ch R = 1 ,18813.87,492.371900,492.371900,492.371900
XS GIS Cut Line= 6
748894.718994953833403.431591111749189.949935567833211.940345502
749425.986187377 833150.62776983749493.210101587833120.842560821
749595.628641646833040.081628679 749735.96063238832897.611328617
#Sta/Elev= 30
9499.088322.97839524.368316.86599536.833316.89479563.466328.89769600.304332.5245
9614.552331.63299632.343327.97829650.135 326.1739722.712322.03419742.977317.1627
9766.367314.50659789.477309.12329823.364291.45829834.659287.69879857.047287.4266
9878.834283.36129961.536260.93799983.376256.3378 9993.82252.498910003.93250.7183
10014.05257.352910034.27274.191910054.49284.975110085.24309.613310095.52312.6454
10139.16318.115510273.63318.709310313.74317.618810449.76323.706210500.86319.9446
#Mann= 3 , 0 , 0
9499.088   0.045       09499.088   0.045       010500.86   0.045       0
#XS Ineff= 2 , 0
       0                               0
Bank Sta=9499.088,10500.86
Exp/Cntr=0.3,0.1

Type RM Length L Ch R = 1 ,18321.49,492.371900,492.371900,492.371900
XS GIS Cut Line= 6
749553.093130838833807.624901955749628.498444854833591.095855068
749684.327041229833298.863050428 749723.82212453833144.766646172
749766.877718808833040.882615294749864.104081053832862.539287754
#Sta/Elev= 30
9499.033349.10079512.721 345.6119545.247343.47169556.134341.19799672.531335.5257
9714.104325.6472  9734.8315.78049755.288311.77079765.532304.86379816.717282.9875
9826.858280.0219 9847.14  279.589857.281277.11929887.704263.24919907.986257.8061
 9968.93254.40579978.015252.34849989.297243.43799999.479240.766610009.68243.4428
10019.88254.580610040.36272.234510060.88284.127810132.95 301.07710185.05304.9204
10249.32312.784510315.66316.094310372.09315.175810406.47304.960310500.95305.2069
#Mann= 3 , 0 , 0
9499.033    0.04       09499.033    0.04       010500.95    0.04       0
#XS Ineff= 2 , 0
       0                               0
Bank Sta=9499.033,10500.95
Exp/Cntr=0.3,0.1

Type RM Length L Ch R = 1 ,17829.12,492.371900,492.371900,492.371900
XS GIS Cut Line= 6
749976.487168476833918.836260327750067.378053956833701.828342159
750151.415908554833406.801967965750161.734408128 833334.34319806
750178.041127382833093.286438227750198.182332848832950.140051503
#Sta/Elev= 30
9499.055310.57989624.117304.28379645.652301.5835 9656.42298.1586 9709.87272.0267
9741.602260.97439772.932239.29449783.376234.75439886.871233.64369897.176236.6612
9917.786 255.8659928.091255.49029948.701248.6482 9979.98233.054410001.47227.3078
10012.18227.921810053.51240.7695 10083.9246.606210114.08247.791810144.14245.4425
10164.17 247.98110194.22257.385110204.24  263.4210214.26264.030410234.29276.2437
10264.34283.501610294.43296.880410445.41300.5053 10485.9303.732510500.95308.7786
#Mann= 3 , 0 , 0
9499.055    0.12       09499.055    0.12       010500.95    0.12       0
#XS Ineff= 2 , 0
       09930.397                       0
Bank Sta=9499.055,10500.95
Exp/Cntr=0.3,0.1

Type RM Length L Ch R = 1 ,17336.75,492.372000,492.372000,492.372000
XS GIS Cut Line= 6
750223.208678302833881.265202575750441.785925329833579.185374041
750596.681647934 833489.88899972750682.747796019 833408.12510869
750755.897035282833281.022065997750813.203451975833109.042480662
#Sta/Elev= 30
9499.149294.39339748.889287.77969761.425282.12329799.032268.32929862.137249.9333
9903.555241.00079928.529234.28919951.981231.04519963.025231.87779974.068230.6746
9984.714228.63839995.111223.844610005.52223.055510016.12226.080710027.86227.8271
10051.33229.8574 10063.8229.933810076.43231.563210086.32235.151310122.74252.3891
10145.85267.637610163.12 280.68910176.25287.443410188.66287.141710210.83291.0084
10247.98291.388510292.95288.832610315.02286.286210400.71282.516610500.81  285.61
#Mann= 3 , 0 , 0
9499.149    0.12       09499.149    0.12       010500.81    0.12       0
#XS Ineff= 2 , 0
       0                               0
Bank Sta=9499.149,10500.81
Exp/Cntr=0.3,0.1

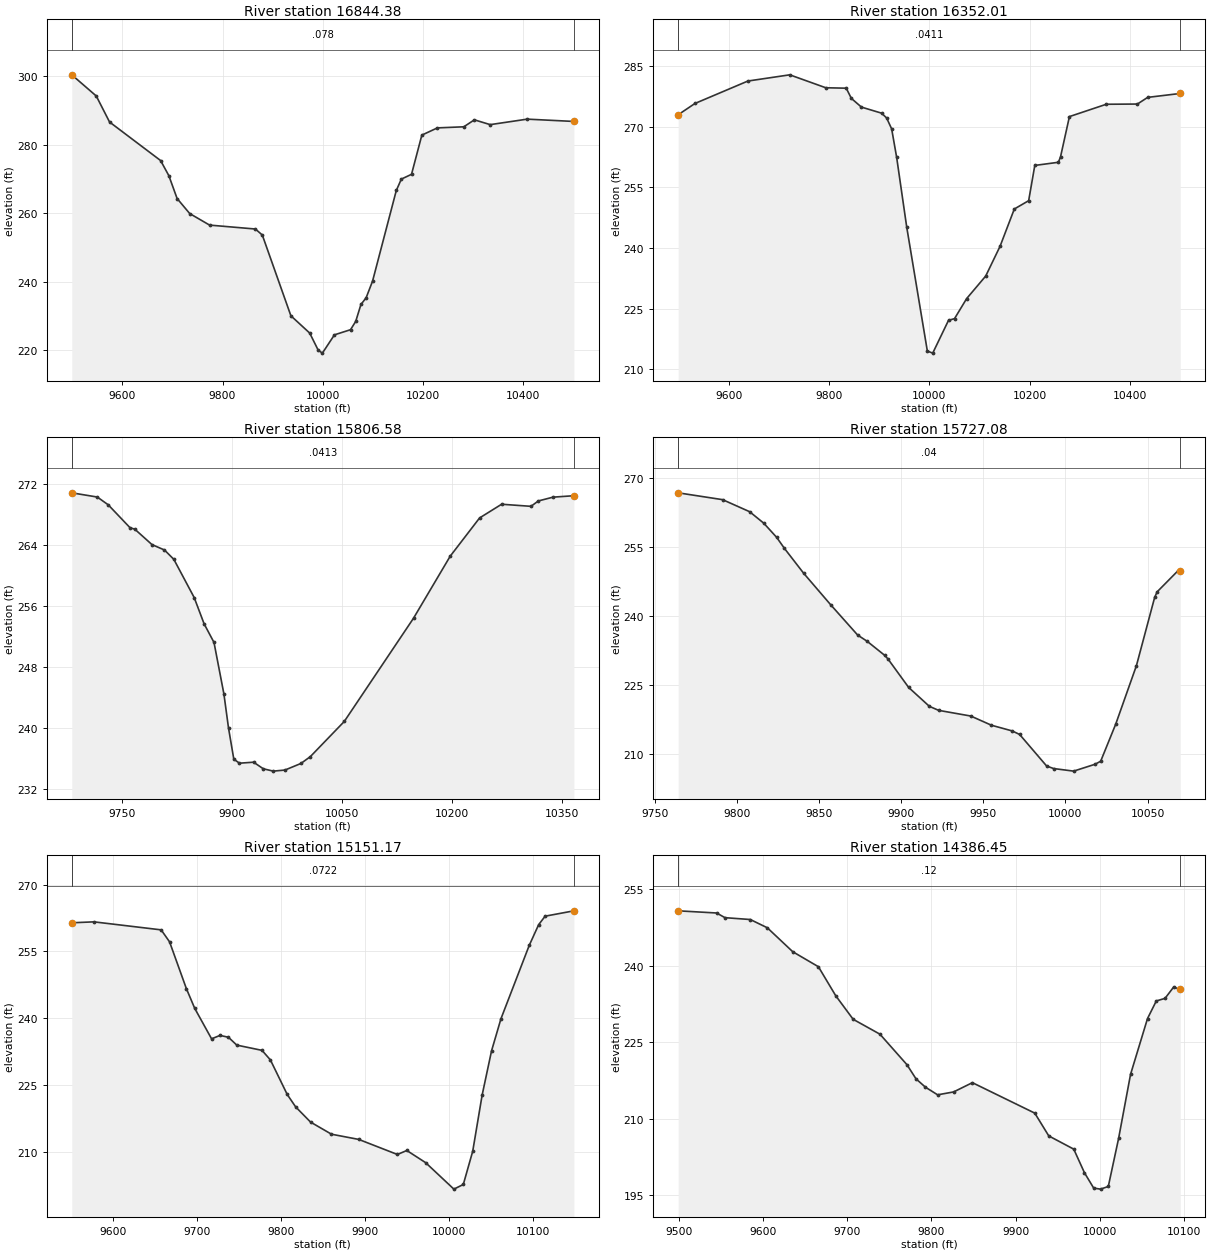
Type RM Length L Ch R = 1 ,16844.38,492.371900,492.371900,492.371900
XS GIS Cut Line= 6
750581.545252022834154.944598073750734.713714421833946.174970865
750863.565588392833804.256522344750826.439355985833676.099124948
750824.808463011833607.541149371750924.532994012 833275.72272924
#Sta/Elev= 30
9499.222300.46469548.112294.27139574.585286.6703 9676.42275.40229692.871  270.98
9709.321264.30099734.493259.90329774.149256.52829865.508255.38199879.286253.6239
9936.324230.01319973.852224.95919990.814219.95269999.126219.096210023.17224.4429
10055.28225.943510065.66 228.38210076.04 233.32610086.38235.265910099.26240.1662
 10146.6266.657110156.65269.977310176.94271.377210197.54282.841410228.58 284.951
10281.25285.268610302.32287.306310333.93285.902810407.67287.507910500.86286.8336
#Mann= 3 , 0 , 0
9499.222   0.078       09499.222   0.078       010500.86   0.078       0
#XS Ineff= 2 , 0
       0                               0
Bank Sta=9499.222,10500.86
Exp/Cntr=0.3,0.1

Type RM Length L Ch R = 1 ,16352.01,545.424900,545.424900,545.424900
XS GIS Cut Line= 6
750893.906816714834426.493884739750988.467536135834095.995496234
750974.790212439 833893.50056053751070.492876098833841.955558873
751119.185580378833785.330505389751191.004065118 833530.69881476
#Sta/Elev= 30
9499.164273.02719532.641275.82219638.252281.38429721.656282.92139793.562279.7138
9834.311279.61119844.486277.08419864.617 274.9219904.868273.41679914.869272.2221
9924.869269.5232 9934.87262.44379954.897245.19179996.048214.462910006.78213.9448
10038.27222.073610050.22222.490210074.42227.461810112.43233.048510141.08 240.434
10169.47249.663710198.08 251.72810210.32260.465810257.41261.246610261.64 262.602
10279.37272.571410352.88 275.62710414.97275.679810435.36277.330810500.49278.3043
#Mann= 3 , 0 , 0
9499.164  0.0411       09499.164  0.0411       010500.49  0.0411       0
#XS Ineff= 2 , 0
       0                               0
Bank Sta=9499.164,10500.49
Exp/Cntr=0.3,0.1

Type RM Length L Ch R = 1 ,15806.58,79.504900,79.504900,79.504900
XS GIS Cut Line= 5
751281.671398073834118.623292193751452.754169941833929.688405007
751525.650307477833838.940152094751534.576365173833730.339783862
751534.576365173833526.528133914
#Sta/Elev= 30
9681.758270.87619716.513270.32439731.412269.30599761.208266.29359767.589 266.112
9791.005 264.0919808.061263.37969820.801262.15699848.533257.14779862.023253.7062
9875.514 251.2629889.004244.51619895.293240.04519902.495 235.9649910.191235.4345
9929.476235.56599942.655234.70319956.196234.39479972.164 234.5369993.962235.4001
10006.79236.298610053.04240.9119 10147.3254.435910197.35262.577310237.35267.5851
10267.35269.380510307.35269.105910317.35269.810410337.35270.308910365.82270.4977
#Mann= 3 , 0 , 0
9681.758  0.0413       09681.758  0.0413       010365.82  0.0413       0
#XS Ineff= 2 , 0
       09938.488         10024.2       0
Bank Sta=9681.758,10365.82
Exp/Cntr=0.3,0.1

Type RM Length L Ch R = 1 ,15727.08,575.906000,575.906000,575.906000
XS GIS Cut Line= 2
751418.537615538834096.308148026751604.497150213833853.816914856
#Sta/Elev= 30
9764.323266.74279791.375265.25389807.808262.63479816.379260.14379824.241257.0582
9828.981254.65189840.674249.24399857.107242.3913 9873.54235.79149879.389234.4123
9889.973231.38099891.991230.59149904.593224.38289917.195220.27019922.839219.3976
9942.399218.15979955.001216.15539967.603214.91849972.138214.14659988.571207.2768
9992.807206.7318   10005206.169310018.01207.662210021.44208.320110030.61216.4029
10043.21229.1321 10054.3 243.98510055.82245.195810068.42249.757510069.91249.7557
#Mann= 3 , 0 , 0
9764.323    0.04       09764.323    0.04       010069.91    0.04       0
#XS Ineff= 2 , 0
       0                               0
Bank Sta=9764.323,10069.91
Exp/Cntr=0.3,0.1

Type RM Length L Ch R = 1 ,15151.17,764.715700,764.715700,764.715700
XS GIS Cut Line= 3
751794.919713676834151.352170289751800.870418757833867.206001356
751659.541172445833587.522861257
#Sta/Elev= 30
9550.751261.42949577.109261.64119657.126259.83929667.128257.14659687.133246.6326
9697.135242.16859717.139235.34499727.141236.10949737.144 235.7029747.146233.9303
9777.152232.75119787.155230.59649807.159222.83319817.161220.05029834.959216.6232
9859.839213.90269892.321212.72979938.269209.34469949.473210.24129971.882207.5071
10005.49201.5566 10016.7202.6025 10027.9210.069810039.11222.692710050.31232.6462
10061.52239.862710095.13256.337410106.33260.992710114.05262.914110148.32264.1189
#Mann= 3 , 0 , 0
9550.751  0.0722       09550.751  0.0722       010148.32  0.0722       0
#XS Ineff= 2 , 0
       0                               0
Bank Sta=9550.751,10148.32
Exp/Cntr=0.3,0.1

Type RM Length L Ch R = 1 ,14386.45,492.371900,492.371900,492.371900
XS GIS Cut Line= 6
752207.824536811834190.597596139752196.838830757834047.160009806
 752157.58904808833917.369781335752098.567323822833808.013231482
751999.102088891 833723.39509756751982.112846419833667.120710525
#Sta/Elev= 30
9499.266250.70189544.896250.27729554.902249.36219584.969248.99979605.125247.3891
9635.359242.7004 9665.86239.76119686.454234.08219707.155229.47229738.962226.5608
9771.003220.59819781.798217.82559792.961216.19429807.472214.69429826.453215.2583
 9848.78217.07319922.909211.11239939.528206.65279969.209204.06299981.944199.4348
9992.913196.4365   10001196.238510010.24196.755610022.48206.158110036.68218.7007
10056.84229.625310067.28233.066310077.64233.569410087.79235.764510095.79235.3472
#Mann= 3 , 0 , 0
9499.266    0.12       09499.266    0.12       010095.79    0.12       0
#XS Ineff= 2 , 0
       0                               0
Bank Sta=9499.266,10095.79
Exp/Cntr=0.3,0.1

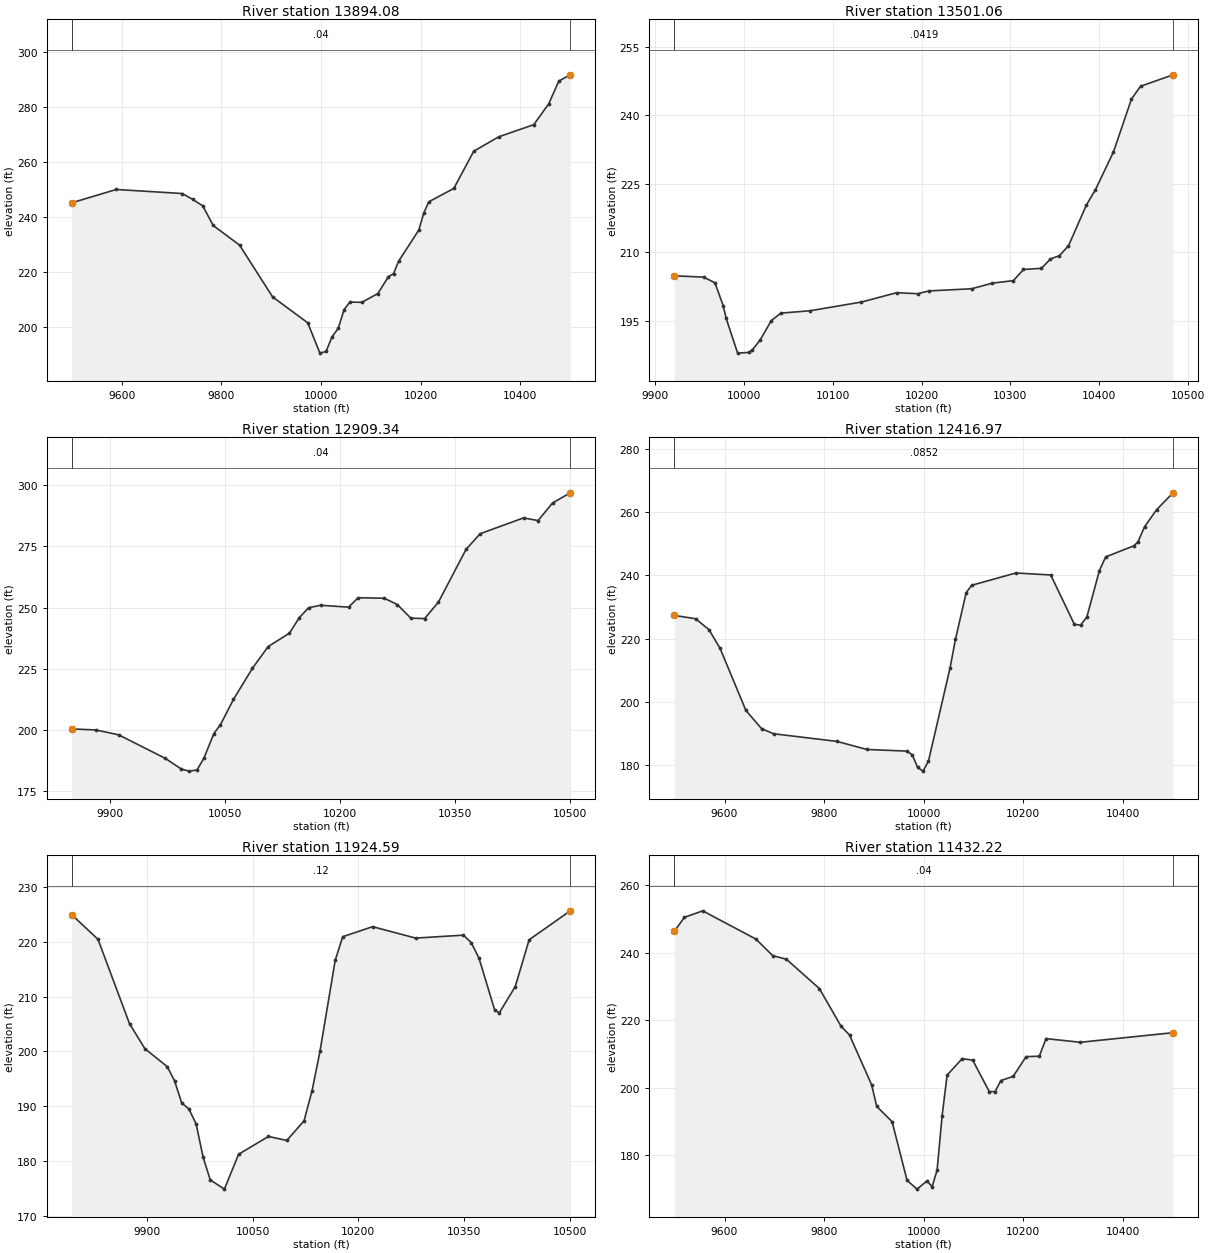
Type RM Length L Ch R = 1 ,13894.08,393.027100,393.027100,393.027100
XS GIS Cut Line= 6
752264.500832935834443.213100275752334.338316669834129.127374603
752376.720814819834039.553130528752460.829774872833912.516507557
752487.110747753833849.846266709752524.793475068833492.107453775
#Sta/Elev= 30
9499.072245.16299588.893 250.0249721.381248.55019742.001246.45549762.621244.0553
9783.473236.92479836.486 229.7669902.835210.91469973.424201.46489997.969 190.423
10010.23191.035510022.47196.434710034.69199.425910046.42206.252910058.14209.0205
10082.22208.921510114.19212.111310135.39218.215910145.83219.371210156.08223.9165
10196.67235.275610206.73241.567810216.75245.552710266.87250.399210306.97263.9557
10357.09269.204410427.51 273.62610457.72281.249810477.86289.517110500.91291.7797
#Mann= 3 , 0 , 0
9499.072    0.04       09499.072    0.04       010500.91    0.04       0
#XS Ineff= 2 , 0
       0                               0
Bank Sta=9499.072,10500.91
Exp/Cntr=0.3,0.1

Type RM Length L Ch R = 1 ,13501.06,591.716800,591.716800,591.716800
XS GIS Cut Line= 4
752811.002610922834158.790551662752574.462082833 833974.31869331
752526.856442004833896.959526896752553.634614974833728.852107584
#Sta/Elev= 30
  9921.9204.85279954.876204.55839967.557203.31429976.847198.31279980.239195.4936
9993.108187.9033 10005.6188.052410009.37 188.54810018.28190.723310030.96195.0379
10041.89196.679110074.41 197.18410132.42199.100310171.98201.144410195.82200.9277
10208.51 201.54110256.29 202.01210279.78203.241810303.26203.792110314.69206.2336
10334.94206.492910345.07208.548610355.19209.275610365.32211.435710385.57220.4001
 10395.7 223.73410415.95232.0235 10436.2243.596710446.33246.388310482.93248.9003
#Mann= 3 , 0 , 0
  9921.9  0.0419       0  9921.9  0.0419       010482.93  0.0419       0
#XS Ineff= 2 , 0
       0                               0
Bank Sta=9921.9,10482.93
Exp/Cntr=0.3,0.1

Type RM Length L Ch R = 1 ,12909.34,492.371900,492.371900,492.371900
XS GIS Cut Line= 6
752866.445307099833924.826702194752876.498006739833893.500082126
752916.538712774833854.322758505753007.433136858833818.394225171
753071.545641785833763.638034023753287.258373573833453.855902939
#Sta/Elev= 30
9849.908200.42149881.789200.00459911.296198.02159972.011 188.4299993.258184.0062
10003.39183.190710013.58183.665910022.63188.493810035.61198.550310044.08202.0747
10061.13212.453610085.85225.173610106.49234.067610134.09239.493710147.14245.8871
10159.32249.933710174.88250.926210211.48250.158610223.85254.009210258.02253.7998
10275.01 251.22510292.63245.665710310.67245.4939 10328.7252.224910364.77273.7634
10383.14280.146310439.83286.617110458.73 285.52410477.63292.703610500.79 296.849
#Mann= 3 , 0 , 0
9849.908    0.04       09849.908    0.04       010500.79    0.04       0
#XS Ineff= 2 , 0
       0                               0
Bank Sta=9849.908,10500.79
Exp/Cntr=0.3,0.1

Type RM Length L Ch R = 1 ,12416.97,492.371900,492.371900,492.371900
XS GIS Cut Line= 6
752866.570738714834370.870941262752997.063558034834219.561444682
 753250.85719246834170.140101475753396.147985358834110.566060376
753557.802930955834017.081225614753707.077295131833892.318598698
#Sta/Elev= 30
9499.147 227.3289541.905226.29729568.786222.82199590.922216.96889642.858197.3241
9674.435191.5662 9698.49189.95469825.634187.54349885.986  184.999966.584184.4717
9977.224183.25319987.865179.29849998.714178.148210009.59181.287310052.95210.7059
10063.79 219.73610085.47234.560710096.31236.848910185.14240.746310255.23240.1146
10302.88 224.47310315.28224.286810327.88226.863710353.06241.528810365.65245.8264
10422.44249.333810430.51250.589310443.76255.367210467.87260.721910500.93266.0682
#Mann= 3 , 0 , 0
9499.147  0.0852       09499.147  0.0852       010500.93  0.0852       0
#XS Ineff= 2 , 0
       0                               0
Bank Sta=9499.147,10500.93
Exp/Cntr=0.3,0.1

Type RM Length L Ch R = 1 ,11924.59,492.372000,492.372000,492.372000
XS GIS Cut Line= 6
753165.111824822834687.342189683 753223.54237485834562.861998729
753238.393921362834453.832130272753257.611865748834412.147015832
753300.435929658834381.581461613753628.417982002834235.458894146
#Sta/Elev= 30
9793.338225.01259830.787220.48469875.503205.0658 9897.35200.50989929.026197.2332
9939.317194.66319949.534 190.6019959.751189.48689969.948186.78379979.985 180.642
9990.023176.544510010.08174.859410030.21181.227410072.56184.4803 10098.6183.7493
10123.07187.334610134.48192.862410145.62200.002510167.24216.635210177.89220.9572
10220.26222.794510281.37220.711110349.04221.245510360.16 219.89210371.28217.0255
10393.53207.547410400.11207.074810422.63211.849210442.38220.408710500.72225.6905
#Mann= 3 , 0 , 0
9793.338    0.12       09793.338    0.12       010500.72    0.12       0
#XS Ineff= 2 , 0
       0                               0
Bank Sta=9793.338,10500.72
Exp/Cntr=0.3,0.1

Type RM Length L Ch R = 1 ,11432.22,492.371900,492.371900,492.371900
XS GIS Cut Line= 6
753136.933958175835071.387935786753367.216735804834820.291996251
753453.330872463834787.840317755753597.479605775834788.683149582
 753690.93199418834737.718906785753893.276482927834499.348331747
#Sta/Elev= 30
9499.202 246.2849519.306250.39189556.109252.34289663.406243.9416 9696.54239.0984
9724.252238.01149790.476229.33179833.806218.22889851.037 215.5689895.269200.8984
9905.771194.42669936.583189.9201 9966.61172.53999986.701169.952910006.84172.4009
10016.89 170.63510026.95175.5853   10037191.636310047.03203.701210077.37208.5985
10098.48 208.11810131.68198.841110143.35198.811710155.03202.093710179.66203.3178
10205.69209.1695 10232.3209.311710245.69214.513310314.72213.426710500.81216.2681
#Mann= 3 , 0 , 0
9499.202    0.04       09499.202    0.04       010500.81    0.04       0
#XS Ineff= 2 , 0
       0                               0
Bank Sta=9499.202,10500.81
Exp/Cntr=0.3,0.1

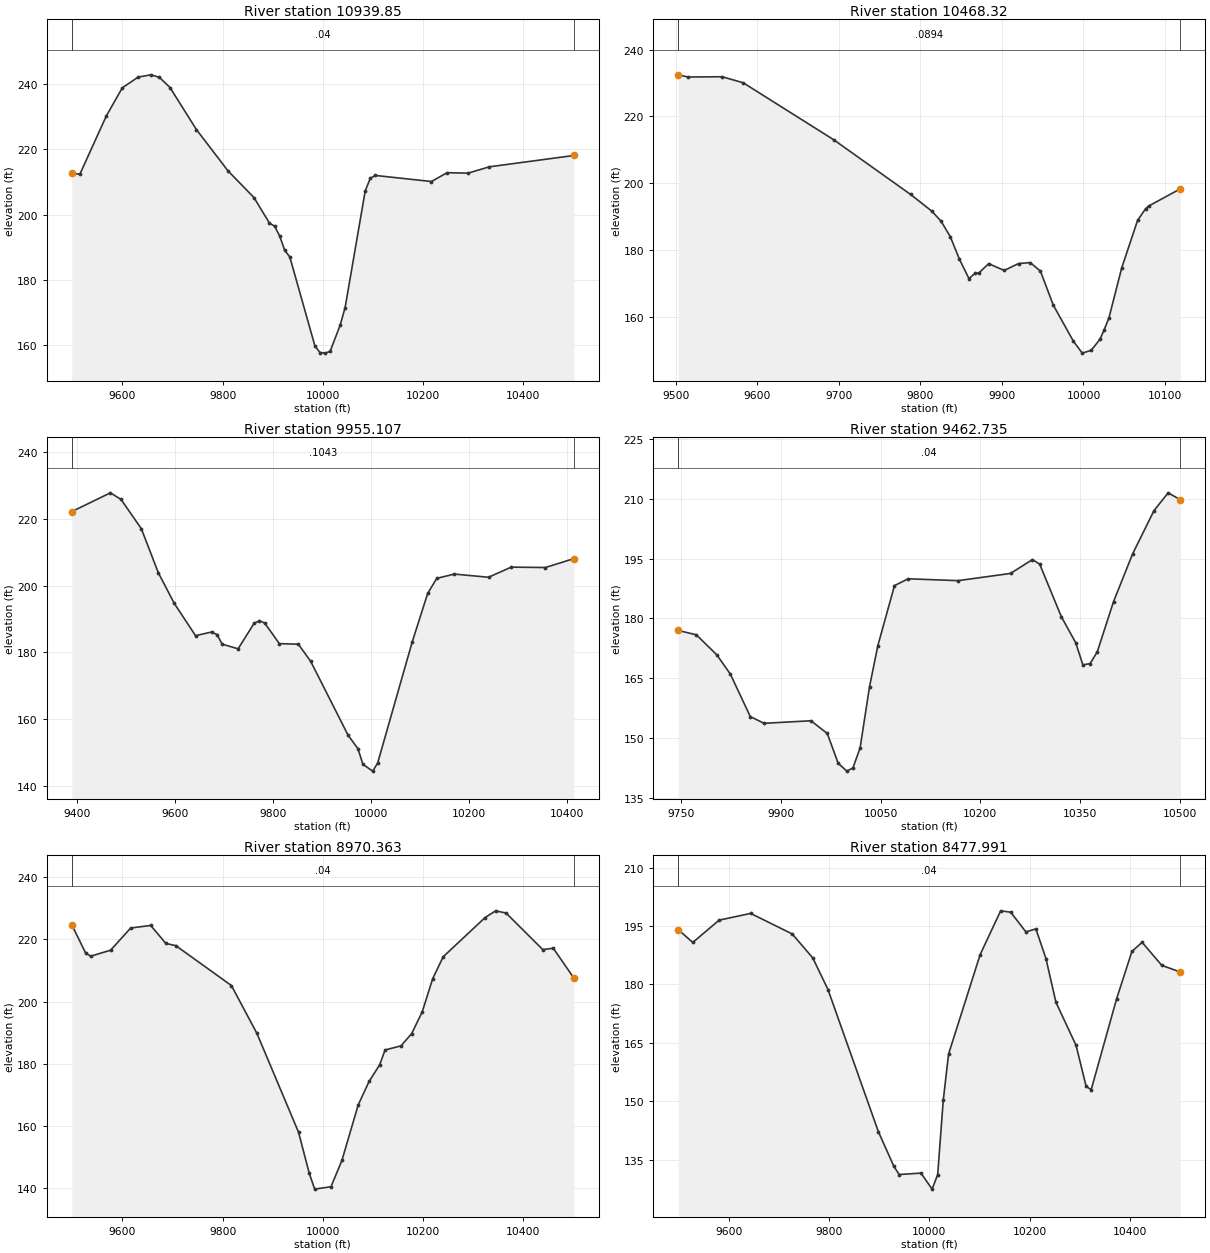
Type RM Length L Ch R = 1 ,10939.85,471.531600,471.531600,471.531600
XS GIS Cut Line= 6
753763.631785365835420.350917596753880.107293216835063.309420369
753893.972079893 834984.84308042753908.045531126 834811.70301027
753928.332290643834715.752081558754020.973009045834457.290051871
#Sta/Elev= 30
9499.031212.57239515.264212.36419568.137230.21649599.861238.78869631.585242.0765
9657.017242.76759673.883242.00559695.032 238.8839747.854225.99229810.755213.3789
9862.584205.19719893.419197.39419903.642196.43499913.848193.45769923.953189.0367
9934.058187.04129984.363159.71049994.395157.748910004.42157.563610014.44158.0681
10034.47166.045110044.49171.501410084.61207.196910094.68  211.0810104.74211.9631
10216.79 210.10510247.96212.805210289.92212.666210332.22214.601610500.96218.0719
#Mann= 3 , 0 , 0
9499.031    0.04       09499.031    0.04       010500.96    0.04       0
#XS Ineff= 2 , 0
       0                               0
Bank Sta=9499.031,10500.96
Exp/Cntr=0.3,0.1

Type RM Length L Ch R = 1 ,10468.32,513.212200,513.212200,513.212200
XS GIS Cut Line= 6
754062.761854745835536.717465733754123.743316939835343.845578258
754190.000803395835206.045605204754247.691902923835129.970349126
754352.441034537835067.961999235754366.674651178835029.543735939
#Sta/Elev= 30
9502.822232.43689515.023231.78199556.675231.86729582.576 230.0539693.361213.0353
9787.924196.62879813.928191.6298  9825.3188.62659836.673183.96749847.728177.2941
9859.493171.44919867.116173.03789871.588173.11219883.682175.91359902.674 173.883
 9920.47175.95479934.737176.22259947.175173.69019963.003163.48539987.462152.7797
9998.516149.131810009.45149.969510020.37 153.31310025.49156.178510031.28159.7046
 10046.9174.620810066.45188.911710076.33192.388710080.07193.169310118.81198.3087
#Mann= 3 , 0 , 0
9502.822  0.0894       09502.822  0.0894       010118.81  0.0894       0
#XS Ineff= 2 , 0
       0                               0
Bank Sta=9502.822,10118.81
Exp/Cntr=0.3,0.1

Type RM Length L Ch R = 1 ,9955.107,492.372000,492.372000,492.372000
XS GIS Cut Line= 6
754509.928919345835387.611156523 754674.29815957834997.406649992
754585.729263932834955.980306774 754448.25376457834946.261166573
754383.764628559834930.786123037754233.221131802 834675.01421982
#Sta/Elev= 30
9389.473222.22759468.263227.85979489.965225.87639531.334217.11159565.922203.9256
9598.475194.72469641.879185.03929674.432186.13089685.893185.36699696.134 182.506
9728.687181.1042 9761.24188.72769772.091189.53629782.942188.81249812.884182.6425
9851.477182.49879876.717177.33879953.142155.16049973.169151.14749983.178146.4889
 10003.2144.437810013.22146.835710083.79183.170610115.28197.696710133.87202.2293
10169.72203.505510239.34202.550510285.76205.586510355.38 205.47110413.38208.1358
#Mann= 3 , 0 , 0
9389.473  0.1043       09389.473  0.1043       010413.38  0.1043       0
#XS Ineff= 2 , 0
       0                               0
Bank Sta=9389.473,10413.38
Exp/Cntr=0.3,0.1

Type RM Length L Ch R = 1 ,9462.735,492.371900,492.371900,492.371900
XS GIS Cut Line= 6
754706.209253961834991.345678706 754688.02890849834908.911576818
754696.222744156834856.342614376754870.499227359834603.734342733
754921.001049763834497.078733703  754989.8975343834317.878580959
#Sta/Elev= 30
9745.318176.95119772.557175.86319803.414170.82749823.745166.0001 9853.81155.3329
9874.426153.64739945.094154.2887 9969.65151.09589985.975143.6375    9999 141.645
10008.24142.447810019.02147.468210033.26162.870510045.78173.1703 10070.8188.2113
10091.39189.919610166.39189.455710245.46191.264610278.35194.741910289.31193.5975
10321.98180.380710343.54173.862910354.33168.306310365.11168.635210375.89 171.537
10400.52184.2166 10429.3  196.2210461.38207.0436 10482.7211.496510500.96209.7588
#Mann= 3 , 0 , 0
9745.318    0.04       09745.318    0.04       010500.96    0.04       0
#XS Ineff= 2 , 0
       0                               0
Bank Sta=9745.318,10500.96
Exp/Cntr=0.3,0.1

Type RM Length L Ch R = 1 ,8970.363,492.371900,492.371900,492.371900
XS GIS Cut Line= 6
755084.277835244835452.561323039755090.695470833835238.462100426
755115.266501418835070.284884488755136.931254758834998.428092789
755219.804008717834789.124815169755312.839205505 834485.76507593
#Sta/Elev= 30
9499.072224.71629526.636215.65639536.637214.59469576.642216.54469616.646223.6626
9656.686224.47979686.729 218.7129706.757217.98819817.573205.18799868.426189.8523
9951.549158.08879973.002144.86389983.816139.792510016.36140.563610038.09148.9914
10070.69166.851410092.31174.364410113.59179.742810124.23184.489110156.14185.8084
10177.42 189.76510198.44196.743610219.36207.411110240.28 214.42910323.96 227.029
10344.88229.1774 10365.8228.464210439.01216.717310459.93217.168910500.97207.5926
#Mann= 3 , 0 , 0
9499.072    0.04       09499.072    0.04       010500.97    0.04       0
#XS Ineff= 2 , 0
       0                               0
Bank Sta=9499.072,10500.97
Exp/Cntr=0.3,0.1

Type RM Length L Ch R = 1 ,8477.991,492.371900,492.371900,492.371900
XS GIS Cut Line= 6
755557.015851414835432.599852456755639.535657256835113.346233392
755630.386147612835023.851603357755571.111881119834879.325134261
755552.148977354834773.533074877755593.869354335834460.973883443
#Sta/Elev= 30
9499.153194.0472 9528.18190.76339580.765196.49589643.654198.22169726.674 192.933
9767.668186.76639797.959178.6449 9898.43142.15719929.432133.22439940.003131.1405
9983.413131.505810005.65127.388710016.79131.117610027.85 150.16810038.51162.1033
10101.54187.646210142.41198.885210162.55198.532410192.72193.479110212.73194.2421
10232.74186.636810252.74175.381310292.91164.3086   10313  153.7610323.05152.9423
10373.76176.285210404.26188.444210424.59190.798810463.91 184.87610500.85183.1593
#Mann= 3 , 0 , 0
9499.153    0.04       09499.153    0.04       010500.85    0.04       0
#XS Ineff= 2 , 0
       0                               0
Bank Sta=9499.153,10500.85
Exp/Cntr=0.3,0.1

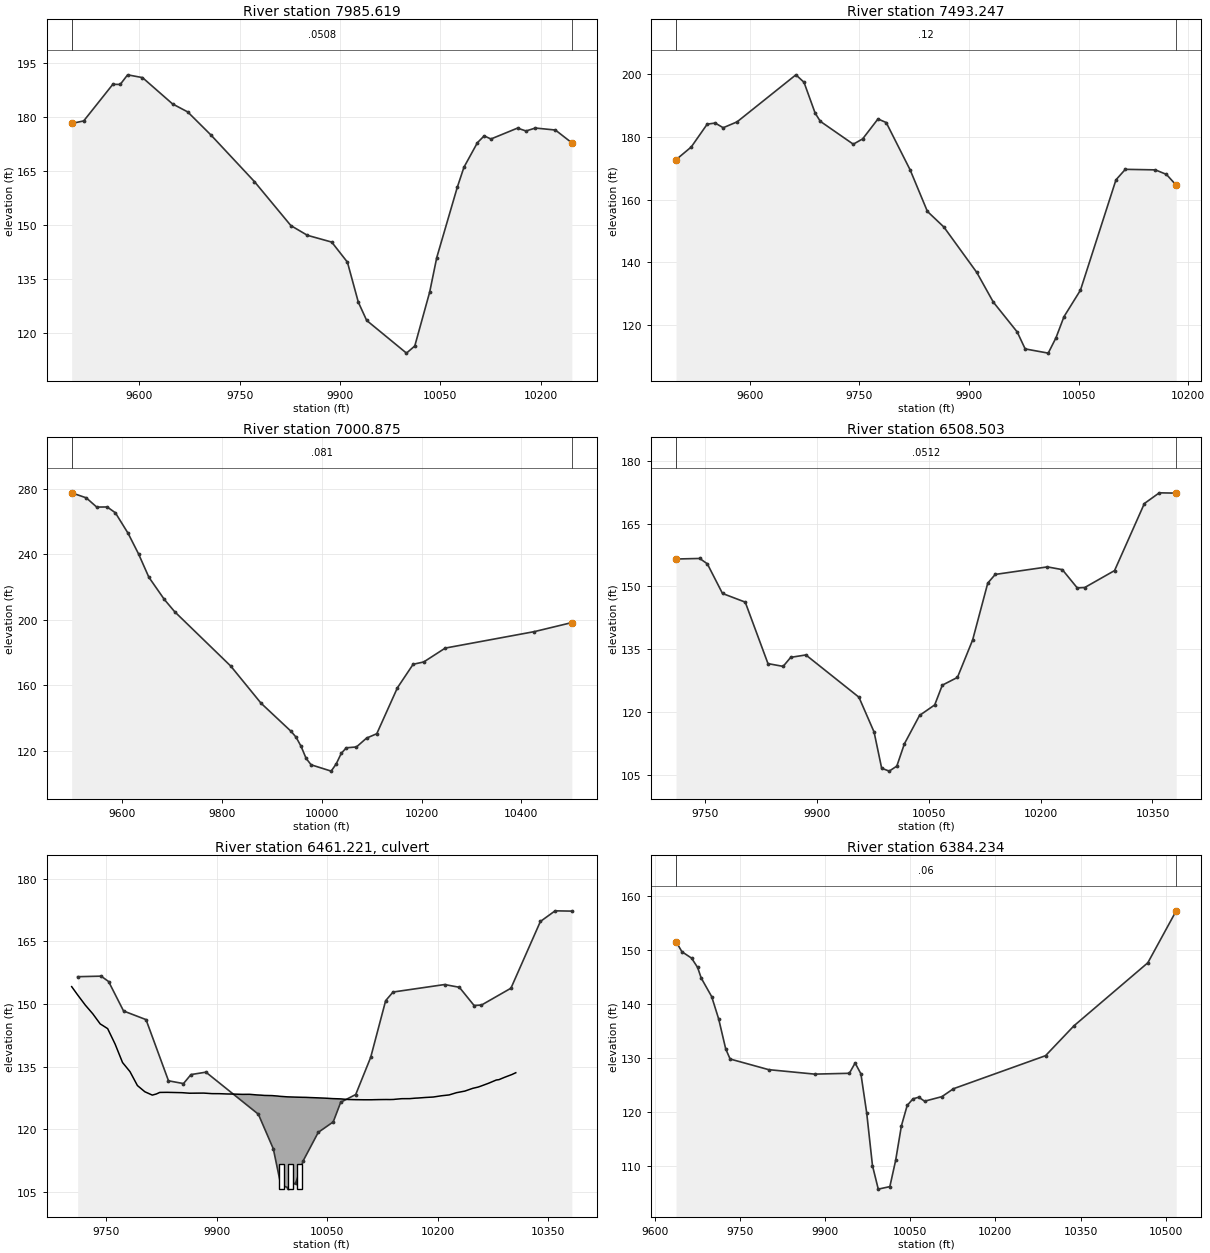
Type RM Length L Ch R = 1 ,7985.619,492.372000,492.372000,492.372000
XS GIS Cut Line= 6
755602.210483305835411.580311035755701.928858645835215.079034829
755813.878161507835109.878164334755884.841168798835074.955793605
756015.147423388835119.922832175756156.642498562835070.953842795
#Sta/Elev= 30
 9499.25178.29579517.258179.0094 9560.71189.16859571.754189.13439582.798191.8041
9604.982191.03589649.881183.72839672.585181.49869707.226175.09489772.128162.1677
9826.609 149.937 9851.28147.23849887.599145.35739911.043139.78969927.363128.6609
9939.816123.5997 9999.27114.519310011.67116.502210033.89131.453510044.49141.0597
10075.13 160.56410085.13166.159310105.21172.956910115.28174.846410125.46 173.989
 10165.1  177.0110177.75176.211510191.79177.027310221.65176.475910246.23172.9214
#Mann= 3 , 0 , 0
 9499.25  0.0508       0 9499.25  0.0508       010246.23  0.0508       0
#XS Ineff= 2 , 0
       0                               0
Bank Sta=9499.25,10246.23
Exp/Cntr=0.3,0.1

Type RM Length L Ch R = 1 ,7493.247,492.371900,492.371900,492.371900
XS GIS Cut Line= 6
755925.030252017835924.001096372 756003.51281791835754.200571319
756118.522136591835532.961833406756149.750885102835450.395932862
 756166.53262324835418.071741227756243.800903888835322.229670858
#Sta/Elev= 30
 9499.05172.72549519.836176.78229541.715184.08349552.655184.42439563.594182.9337
9582.558184.80629663.081199.82149674.162197.44759689.354187.62739696.499184.9763
9741.581177.68049754.395179.36729775.392185.73059786.663184.59499819.437169.4593
9843.015156.22659865.556151.24749910.638136.73229933.179127.28939965.919117.7462
9976.807112.331310008.38110.986110018.97115.869510029.93122.619410052.46131.0752
10101.08166.305610113.88 169.65510154.99169.483610170.16168.032910183.51164.5973
#Mann= 3 , 0 , 0
 9499.05    0.12       0 9499.05    0.12       010183.51    0.12       0
#XS Ineff= 2 , 0
       09820.269                       0
Bank Sta=9499.05,10183.51
Exp/Cntr=0.3,0.1

Type RM Length L Ch R = 1 ,7000.875,492.371900,492.371900,492.371900
XS GIS Cut Line= 6
756488.919390955836032.891039359756561.742114991835769.967587982
756593.791330555835496.505001685756613.669338575835401.378314542
756673.148984589835248.630510978756765.208737545835080.208411688
#Sta/Elev= 30
9499.039277.61439528.258274.55119549.211268.90989570.163268.98379586.542265.4363
9612.068252.88479632.996240.3021 9653.67 226.062 9684.68212.47369705.354205.0032
9817.751 171.7739878.357149.11939938.574131.91269948.589128.32999958.604 122.744
9968.619115.42359978.634111.493410018.89107.621810028.97112.061510039.05  118.46
10049.14121.868910069.44122.381510089.74127.792710110.21  130.4710151.55158.5285
10183.04172.896310204.24174.299310247.32182.774810426.12192.854410500.94198.3633
#Mann= 3 , 0 , 0
9499.039   0.081       09499.039   0.081       010500.94   0.081       0
#XS Ineff= 2 , 0
       0                               0
Bank Sta=9499.039,10500.94
Exp/Cntr=0.3,0.1

Type RM Length L Ch R = 1 ,6508.503,124.268900,124.268900,124.268900
XS GIS Cut Line= 3
756971.372620523 836036.29867886757046.514365733835623.533750102
757048.918812126835372.324487701
#Sta/Elev= 30
9711.059  156.539742.872156.66269753.036155.37529773.365 148.3119803.858146.2423
9834.351131.5754 9854.68130.91279864.844133.06969885.173133.64449956.323123.5637
9976.652 115.2519986.816106.61819996.981105.924710007.14 107.12310017.31112.4421
10037.64119.214210057.97121.724310068.13126.429810088.46128.286310108.79137.1967
10129.12150.785510139.14152.852710209.14154.650610229.15153.991810249.15149.6259
10259.15149.728110299.15153.768410339.15169.770910359.15172.319810381.83172.2497
#Mann= 3 , 0 , 0
9711.059  0.0512       09711.059  0.0512       010381.83  0.0512       0
#XS Ineff= 2 , 0
       0                               0
Bank Sta=9711.059,10381.83
Exp/Cntr=0.3,0.1

Type RM Length L Ch R = 2 ,6461.221,,,
Bridge Culvert--1,0,-1,-1, 0
Deck Dist Width WeirC Skew NumUp NumDn MinLoCord MaxHiCord MaxSubmerge Is_Ogee
30.134,64,2.6,0,78,78, , , 0.95, 0, 0,0,,
 9702.93 9711.37 9721.47 9731.56 9741.66 9745.32 9751.76 9761.85 9771.95 9782.05
 9792.15 9802.24 9812.34 9817.76 9822.44 9832.53 9842.63 9852.73 9855.86 9862.87
 9873.04 9882.20 9883.20 9893.37 9903.53 9913.70 9923.87 9934.03 9937.75 9944.20
 9954.36 9959.75 9964.62 9974.99 9982.67 9985.36 9995.7210006.0910016.4610020.62
10026.8210037.1910047.5610057.9210058.5710068.2910074.5210078.6110088.8710099.13
10100.3910109.4010119.6610129.9210135.0310140.3910141.3710151.0810161.7710169.67
10172.4610183.1510193.8410197.9710204.5310215.2210225.9110226.2710236.6010247.29
10254.5710257.9810268.6710279.3610282.8710290.0510300.7410305.73
  154.15  152.08  149.71  147.64  145.21  144.81  144.08  140.39  135.96  133.78
  130.44  128.95  128.15  128.41  128.79  128.81  128.77  128.73  128.69  128.60
  128.62  128.63  128.62  128.50  128.49  128.42  128.39  128.33  128.33  128.34
  128.19  128.14  128.07  128.03  127.92  127.86  127.73  127.67  127.62  127.61
  127.56  127.49  127.41  127.30  127.30  127.24  127.14  127.09  127.05  127.03
  127.03  127.03  127.07  127.09  127.08  127.11  127.14  127.29  127.30  127.42
  127.44  127.58  127.69  127.80  127.98  128.19  128.76  128.76  129.11  129.77
  130.07  130.28  130.98  131.77  131.85  132.38  133.10  133.51
                                                                                
                                                                                
                                                                                
                                                                                
                                                                                
                                                                                
                                                                                
                                                                
 9702.93 9711.37 9721.47 9731.56 9741.66 9745.32 9751.76 9761.85 9771.95 9782.05
 9792.15 9802.24 9812.34 9817.76 9822.44 9832.53 9842.63 9852.73 9855.86 9862.87
 9873.04 9882.20 9883.20 9893.37 9903.53 9913.70 9923.87 9934.03 9937.75 9944.20
 9954.36 9959.75 9964.62 9974.99 9982.67 9985.36 9995.7210006.0910016.4610020.62
10026.8210037.1910047.5610057.9210058.5710068.2910074.5210078.6110088.8710099.13
10100.3910109.4010119.6610129.9210135.0310140.3910141.3710151.0810161.7710169.67
10172.4610183.1510193.8410197.9710204.5310215.2210225.9110226.2710236.6010247.29
10254.5710257.9810268.6710279.3610282.8710290.0510300.7410305.73
  154.15  152.08  149.71  147.64  145.21  144.81  144.08  140.39  135.96  133.78
  130.44  128.95  128.15  128.41  128.79  128.81  128.77  128.73  128.69  128.60
  128.62  128.63  128.62  128.50  128.49  128.42  128.39  128.33  128.33  128.34
  128.19  128.14  128.07  128.03  127.92  127.86  127.73  127.67  127.62  127.61
  127.56  127.49  127.41  127.30  127.30  127.24  127.14  127.09  127.05  127.03
  127.03  127.03  127.07  127.09  127.08  127.11  127.14  127.29  127.30  127.42
  127.44  127.58  127.69  127.80  127.98  128.19  128.76  128.76  129.11  129.77
  130.07  130.28  130.98  131.77  131.85  132.38  133.10  133.51
                                                                                
                                                                                
                                                                                
                                                                                
                                                                                
                                                                                
                                                                                
                                                                
BR Coef=-1 , 0 , 0 ,, 0 ,,,0.8,-1,,0,
WSPro=,,,, 1 ,,,, 0 ,,,, 0 ,,,,-1 ,-1 ,-1 , 0 , 0 , 0 , 0 , 0
Multiple Barrel Culv=2,6,6,64,0.013,0.5,1,58,1,105.61,105.39,3,Culvert #1, 0, 30.134
 9988.00 9988.0010000.0010000.0010012.0010012.00
Culvert Bottom n=0.013
BC Design=,, 0 ,, 0 ,,,,,,

Type RM Length L Ch R = 1 ,6384.234,393.489300,393.489300,393.489300
XS GIS Cut Line= 4
757008.910011947  836105.6859781757106.734728962835971.461366415
 757189.77198875835546.037597165757198.871962368835265.075909972
#Sta/Elev= 30
9637.777151.51359648.117149.63739665.096148.45499675.748 146.7339682.074144.7668
9700.496 141.3349712.871137.18069725.245 131.6369733.009129.77069800.922127.8003
9881.772126.97469942.904127.12679953.093 129.0319963.281127.0213 9973.47119.7918
9983.659110.01689993.848105.677510014.23106.142610024.41110.9809 10034.6117.4018
10044.79121.185410054.98122.394510065.17122.701410075.36 121.95810105.92122.8042
 10126.3124.274110288.38130.388410338.41135.920710468.48147.594310518.43157.2121
#Mann= 3 , 0 , 0
9637.777    0.06       09637.777    0.06       010518.43    0.06       0
#XS Ineff= 2 , 0
       0                               0
Bank Sta=9637.777,10518.43
Exp/Cntr=0.3,0.1