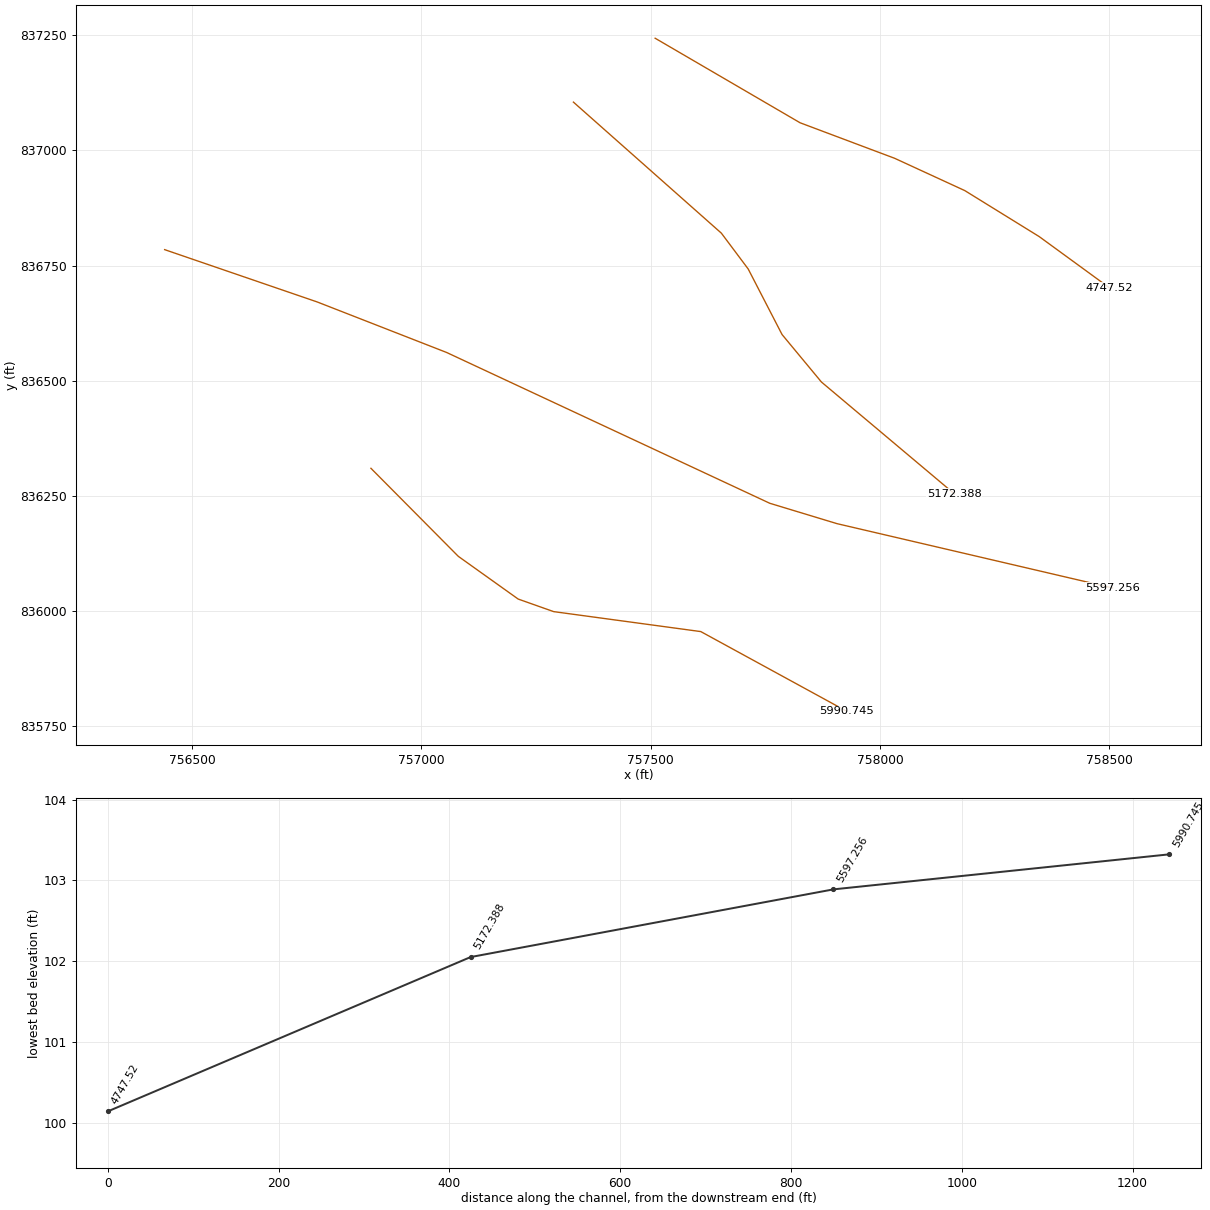
HEC-RAS study 15526_ras.prj: 15526

--- 15526_ras.g01 (geometry) --- (continued)

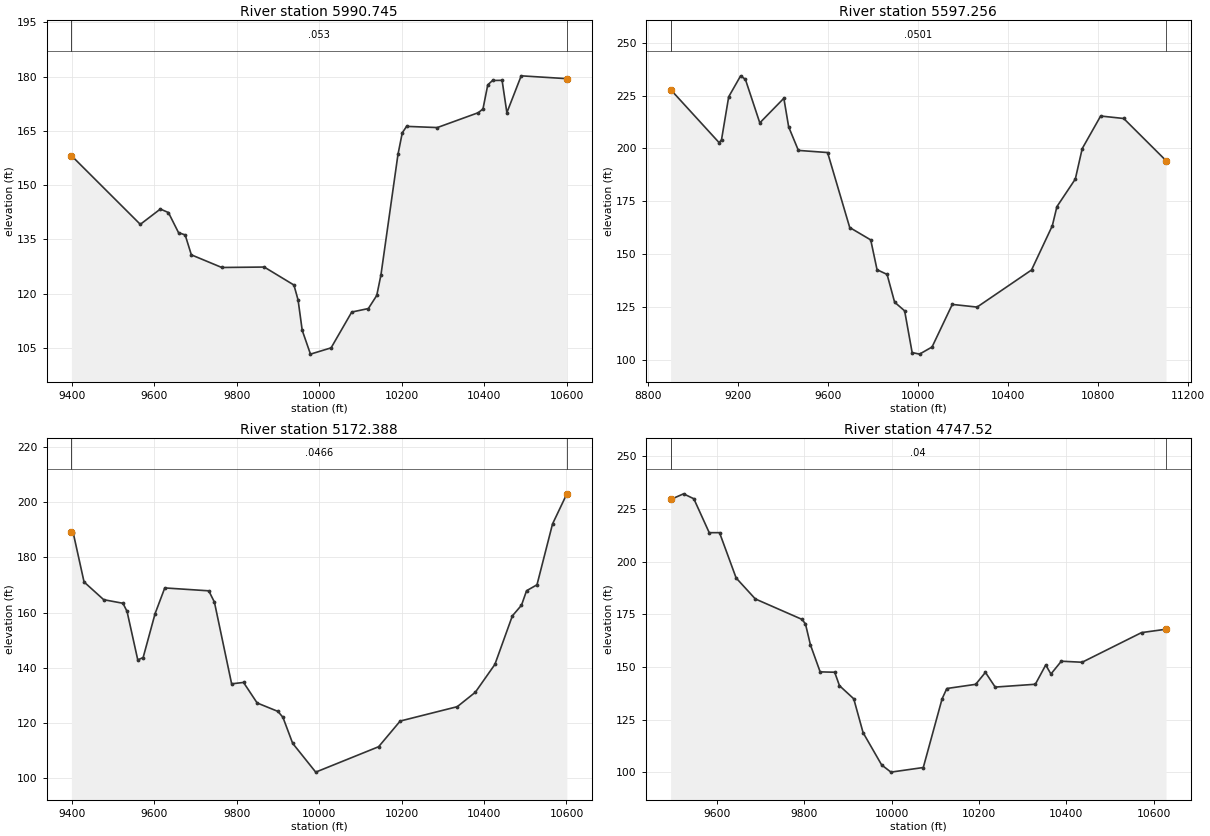
Type RM Length L Ch R = 1 ,5990.745,393.489400,393.489400,393.489400
XS GIS Cut Line= 6
756890.045156775836309.266477423757080.486988714836117.982424637
757211.071587386836025.098394379757288.526639348835997.773107452
757609.286950767835954.400855746757927.593744345835781.122481873
#Sta/Elev= 30
9399.154158.16319566.201 139.1829614.844143.41319634.446142.43829658.922136.8866
9675.011136.26459690.023130.75729763.868127.26299866.807127.38489938.837122.4178
9948.915118.27659958.927109.90949978.936103.321910028.95105.052310079.07114.9469
10119.37115.917110139.75119.540610149.94125.229210191.21158.509810201.64164.4678
10212.08166.258810286.58165.928110386.08170.039910397.42171.094410409.01177.7287
10420.59178.936810443.76178.978610455.35170.0423 10490.1180.224310600.86179.4375
#Mann= 3 , 0 , 0
9399.154   0.053       09399.154   0.053       010600.86   0.053       0
#XS Ineff= 2 , 0
       0                               0
Bank Sta=9399.154,10600.86
Exp/Cntr=0.3,0.1

Type RM Length L Ch R = 1 ,5597.256,424.867600,424.867600,424.867600
XS GIS Cut Line= 6
756440.265175288836784.493299072 756772.77542224 836670.84951627
757055.057115878836561.000919786757759.709304106836233.238755624
757906.218553282836188.988907173758507.067029597836049.194824476
#Sta/Elev= 30
8899.031227.8401 9114.87202.7462 9125.48204.1786 9157.31224.42129210.361 234.312
9231.581232.63669295.572212.09419402.455223.71579423.855210.20099467.004 199.094
 9596.84198.08589695.206162.68079788.613  156.829816.695142.74199861.274140.5383
9894.708127.43059939.287123.32919972.651103.632610005.46 102.88810061.13 106.258
10151.08126.366210261.28125.103810503.26142.619110595.64163.499610616.09172.5348
10697.89185.565710728.56199.952410810.46215.329610912.99214.164811100.95194.2793
#Mann= 3 , 0 , 0
8899.031  0.0501       08899.031  0.0501       011100.95  0.0501       0
#XS Ineff= 2 , 0
       0                               0
Bank Sta=8899.031,11100.95
Exp/Cntr=0.3,0.1

Type RM Length L Ch R = 1 ,5172.388,424.867600,424.867600,424.867600
XS GIS Cut Line= 6
757331.497521668837105.141754993757654.130118259836820.281651143
757712.606171207836742.449429579757786.425289334836599.991979671
757872.310283943836496.761329535758162.282155638836253.729171628
#Sta/Elev= 30
9399.068189.37749403.632188.76289429.693171.10379477.273164.67069524.064163.3634
 9533.94160.42799560.001142.79119573.032143.67049602.034159.62049625.482168.9392
9732.258167.88699745.923163.78519787.672134.11149816.569134.62159849.527127.1725
9900.045124.09569912.096121.95969935.701112.52159991.666  102.0510144.27111.2743
10196.55120.594310335.05125.817310378.81131.044710426.32141.1704 10468.7158.7895
10490.85162.664310503.16167.924110528.45170.078410566.16192.1761 10600.9203.1096
#Mann= 3 , 0 , 0
9399.068  0.0466       09399.068  0.0466       0 10600.9  0.0466       0
#XS Ineff= 2 , 0
       0                               0
Bank Sta=9399.068,10600.9
Exp/Cntr=0.3,0.1

Type RM Length L Ch R = 1 , 4747.52,0.000000,0.000000,0.000000
XS GIS Cut Line= 6
757509.714083247 837243.94958293757825.683994666837060.248234458
 758031.99427435836982.984278074758184.848563619836912.831591361
758347.135216359836812.833255049758500.429767239836701.414174034
#Sta/Elev= 30
9493.716229.41179523.444232.09869546.958229.75759582.229213.67489605.814213.6874
9643.846192.20199687.762182.26289794.713172.56649802.691170.3844 9813.88160.5615
9836.256147.68029869.558 147.5069880.463141.14379913.178134.91959934.611118.8439
 9977.12103.55129998.375100.139510072.45102.324410115.54134.899310126.36139.7864
10192.45141.771310214.79147.448910237.12140.465710329.09141.804610352.88 150.947
10364.79146.664810388.62152.730110436.26152.2412 10572.3166.293910628.34167.8986
#Mann= 3 , 0 , 0
9493.716    0.04       09493.716    0.04       010628.34    0.04       0
#XS Ineff= 2 , 0
       0                               0
Bank Sta=9493.716,10628.34
Exp/Cntr=0.3,0.1